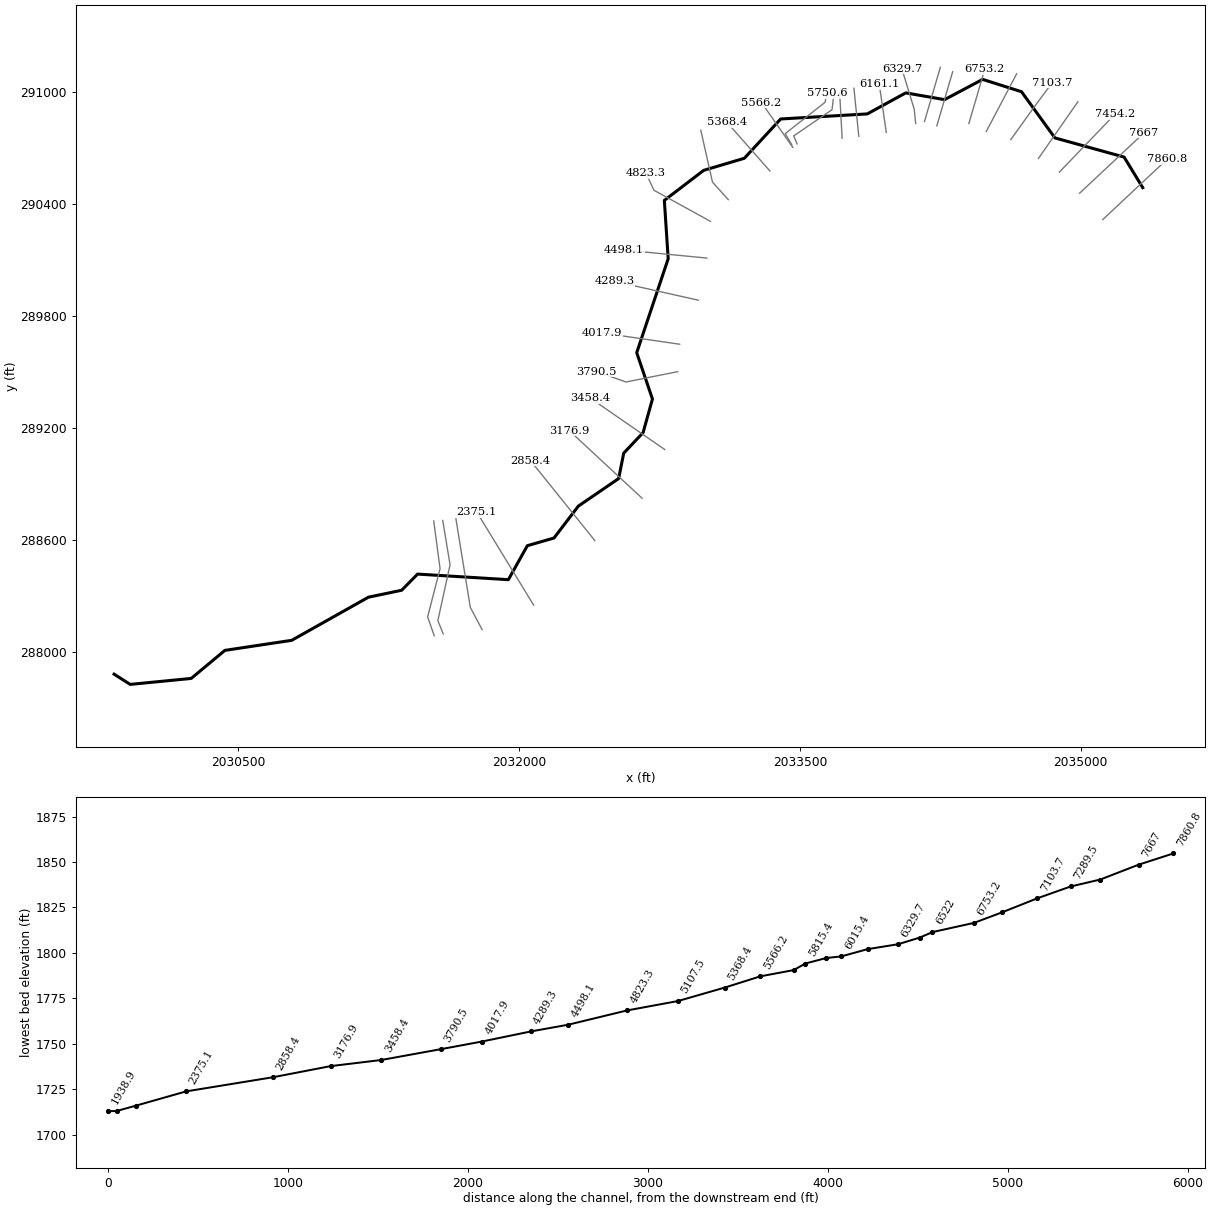
--- RDSPRBR.prj (project) ---

Proj Title=RDSPRBR
Current Plan=p01
Default Exp/Contr=0,0
English Units
Geom File=g01
Flow File=f01
Plan File=p01
BEGIN DESCRIPTION:
END DESCRIPTION:
DSS Export Rating Curves= 0
DSS Export Rating Curve Sorted= 0
DSS Export Volume Flow Curves= 0
DXF OffsetX= 0
DXF OffsetY= 0
DXF ScaleX= 0
DXF ScaleY= 0

--- RDSPRBR.p01 (plan) ---

Plan Title=Floodplain
Program Version=4.00
Geom File=g01
Flow File=f01
K Sum by GR=0
Std Step Tol=0.01
Critical Tol=0.01
Num of Std Step Trials=20
Max Error Tol=0.3
Flow Tol Ratio=0.001
Split Flow NTrial=30
Split Flow Tol=0.02
Split Flow Ratio=0.02
Log Output Level=0
Friction Slope Method=1
Unsteady Friction Slope Method=2
Unsteady Bridges Friction Slope Method=1
Global Log Level=0
CheckData=False
Run HTab=0
Run UNet=0
Run PostProcess=0
UNET Theta=0
UNET Theta Warmup=0
UNET ZTol=0
UNET ZSATol=0
UNET MxIter=0
UNET MaxInSteps=0
UNET DtIC=0
UNET DtMin=0
UNET MaxCRTS=0
UNET WFStab=0
UNET SFStab=0
UNET WFX=0
UNET SFX=0
UNET DSS MLevel=0
UNET DZMax Abort=0
UNET Convert EG Bridges=0
UNET Use Existing IB Tables=0
UNET Froude Limit=0
UNET Froude Power=0
Write IC File=0
Echo Input=False
Echo Output=False
Write Detailed=0

--- RDSPRBR.f01 (steady flow) ---

Flow Title=NFF Regression Equation
Program Version=4.00
Number of Profiles=1
Profile Names=P100yr
River Rch & RM=RDSPRBR,Main      ,7860.8
500.0694
River Rch & RM=RDSPRBR,Main      ,6161.1
528.7468
River Rch & RM=RDSPRBR,Main      ,5931.3
839.3960
River Rch & RM=RDSPRBR,Main      ,4498.1
905.4114
River Rch & RM=RDSPRBR,Main      ,277.8
985.6181
River Rch & RM=RDSPRBR,Main      ,28.2
1206.561
Boundary for River Rch & Prof#=RDSPRBR,Main      ,1
Up Type=0
Dn Type=3
Dn Slope=0.019359

--- RDSPRBR.g01 (geometry) ---

Geom Title=USGS 10m DEM
Program Version=4.10

River Reach=RDSPRBR         ,Main
Reach XY= 30
     2035331.109      290486.593     2035231.748      290650.066
     2034862.359      290752.566     2034683.887      290999.788
     2034476.248       291065.76     2034272.776      290957.427
     2034065.832      290993.538     2033860.276      290881.038
     2033397.776      290853.954     2033203.793      290643.729
     2032986.665      290578.954     2032776.583      290418.295
     2032797.082      290106.038     2032629.026       289603.26
     2032713.054      289355.343     2032663.054      289175.482
     2032559.581       289065.76     2032532.498      288929.649
     2032317.331      288782.375     2032187.359      288611.593
     2032044.998      288570.621     2031943.609      288388.677
     2031458.887      288418.538     2031373.806      288332.076
     2031196.387      288294.927     2030786.777      288064.156
     2030429.884       288010.31     2030249.859      287860.205
     2029924.165       287828.26     2029838.054      287883.121

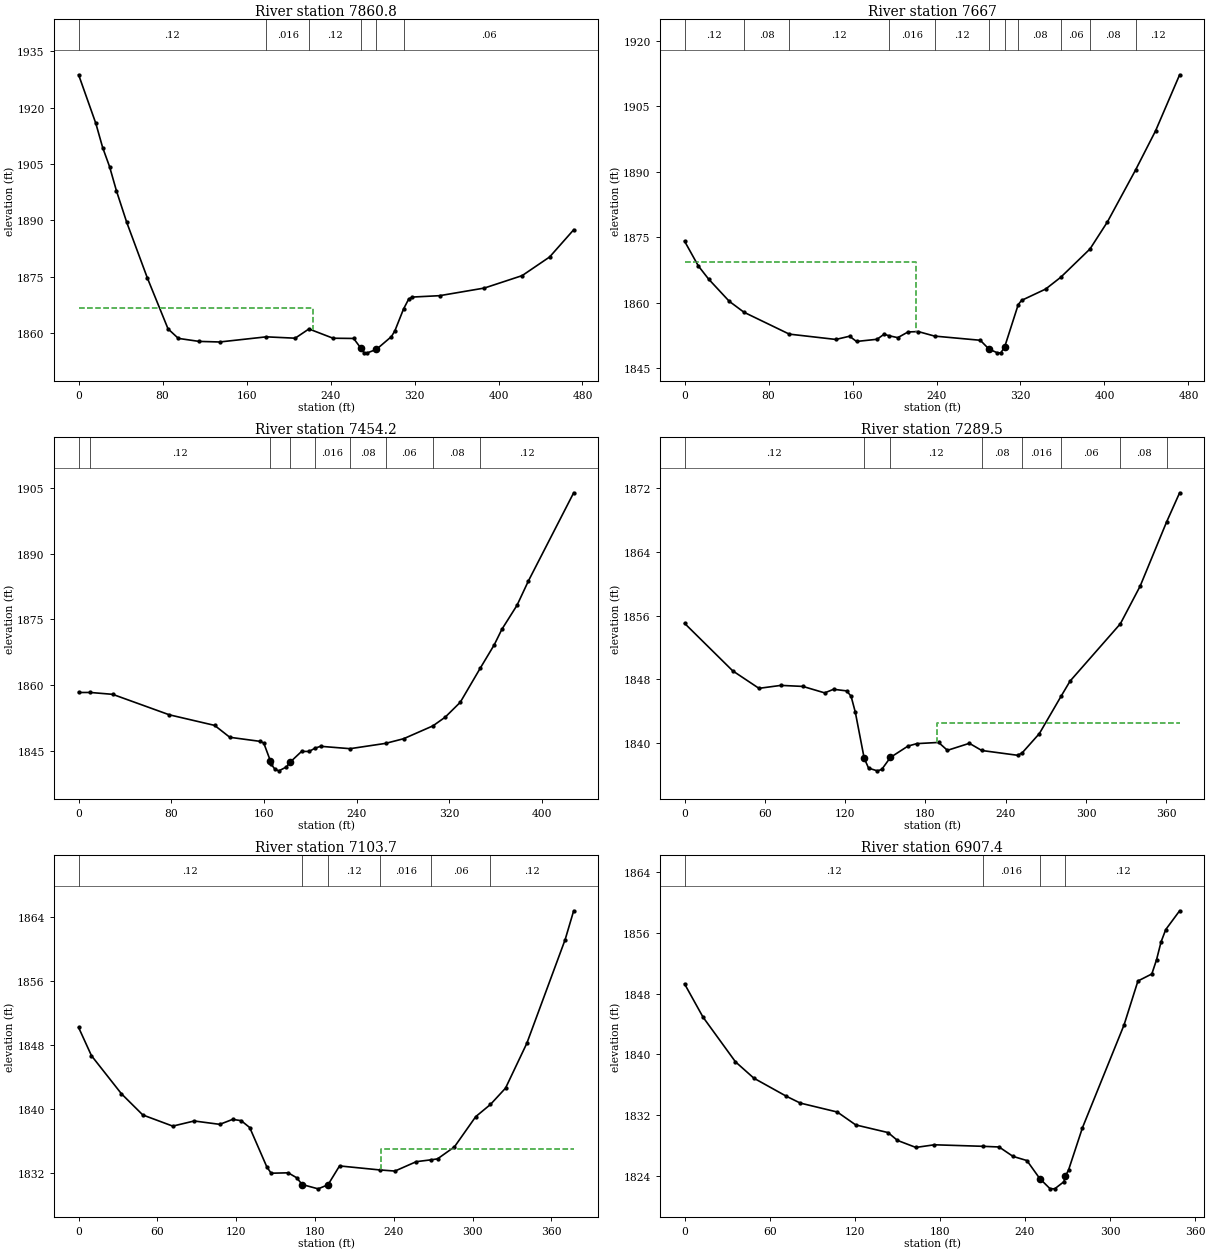
Type RM Length L Ch R = 1 ,7860.8  ,194.1,193.8,193.5
XS GIS Cut Line= 2
     2035117.758      290315.532     2035461.508      290638.449
#Sta/Elev= 30
       0 1928.79    16.4 1915.85    22.9 1909.42    29.5 1904.32      36 1897.93
    45.8 1889.53    65.5 1874.68    85.2 1861.13      95  1858.6   114.6  1857.8
   134.3 1857.64  178.75 1859.01   206.3 1858.65  219.41 1861.11   242.4 1858.64
     262 1858.58   268.7 1856.06   271.8 1854.81   275.1 1854.75   283.7 1855.67
     298 1859.08   301.3 1860.63  309.531866.427   314.4 1869.05   317.7  1869.6
   343.9 1869.97   386.5    1872   422.5 1875.31   448.7 1880.28   471.6 1887.52
#Mann= 6 ,-1 , 0
       0     .12       0  178.75    .016       0  219.41     .12       0
   268.7    .045       0   283.7     .12       0  309.53     .06       0
#XS Ineff= 2 , 0
          223.01 1866.71
Permanent Ineff=
       F       F
Bank Sta=268.7,283.7
XS Rating Curve= 0 ,0
Exp/Cntr=0.3,0.1

Type RM Length L Ch R = 1 ,7667    ,210.1,212.7,212.6
XS GIS Cut Line= 2
      2034994.06      290456.591      2035337.81      290779.508
#Sta/Elev= 30
       0 1874.13    13.1 1868.46    22.9 1865.44    42.6 1860.34   56.611857.835
   99.751852.821   144.1  1851.6   157.2 1852.34   163.8 1851.14   183.4 1851.64
     190 1852.79  194.871852.447   203.1 1852.01   212.9 1853.32   222.7  1853.4
  238.151852.369   281.7 1851.41     290 1849.39     298 1848.53   301.3 1848.53
     305 1849.94  317.851859.586     321 1860.55   343.9 1863.14  358.371865.858
  386.241872.348   402.8 1878.54  429.591890.433   448.7 1899.43   471.6 1912.27
#Mann= 11 ,-1 , 0
       0     .12       0   56.61     .08       0   99.75     .12       0
  194.87    .016       0  238.15     .12       0     290    .045       0
     305     .12       0  317.85     .08       0  358.37     .06       0
  386.24     .08       0  429.59     .12       0
#XS Ineff= 2 , 0
          220.88 1869.45
Permanent Ineff=
       F       F
Bank Sta=290,305
XS Rating Curve= 0 ,0
Exp/Cntr=0.3,0.1

Type RM Length L Ch R = 1 ,7454.2  ,161.2,164.8,168.9
XS GIS Cut Line= 2
     2034886.421      290569.872     2035181.994      290878.466
#Sta/Elev= 30
       0 1858.28    10.21858.286    29.4 1857.86    78.3 1853.18   117.4 1850.76
   130.5 1848.04   156.6 1847.11   159.8 1846.73  165.48 1842.68   166.4 1841.82
   169.6 1840.69   172.9 1840.37   179.4 1841.27   182.7 1842.38   192.4  1844.8
     199 1844.81  203.731845.511   208.8 1845.98  234.311845.436  264.921846.648
   280.5 1847.71  305.821850.651   316.4 1852.64   329.4 1856.04  346.72 1863.87
   358.8 1869.21   365.3 1872.72   378.4 1878.22   388.2 1883.77   427.3 1903.94
#Mann= 9 ,-1 , 0
       0     .08       0    10.2     .12       0  165.48    .045       0
   182.7     .12       0  203.73    .016       0  234.31     .08       0
  264.92     .06       0  305.82     .08       0  346.72     .12       0
Bank Sta=165.48,182.7
XS Rating Curve= 0 ,0
Exp/Cntr=0.3,0.1

Type RM Length L Ch R = 1 ,7289.5  ,186.1,185.8,185.3
XS GIS Cut Line= 2
     2034774.174      290642.602     2034985.111      290946.422
#Sta/Elev= 30
       0 1855.03      36 1849.07    55.6 1846.88      72 1847.25    88.4 1847.12
   104.7 1846.31   111.3 1846.76   121.1 1846.56   124.4  1845.9   127.6 1843.88
   134.2 1838.13   137.5 1836.88     144 1836.54   147.3 1836.71   153.8 1838.22
   166.9 1839.64   173.5 1839.95   189.8  1840.1   196.4 1839.11   212.8 1839.99
  222.041839.091   248.8 1838.49  252.241838.789   265.1 1841.21  281.221845.859
     288 1847.78  325.621854.972   340.4 1859.69  360.121867.717   369.9 1871.39
#Mann= 8 ,-1 , 0
       0     .12       0   134.2    .045       0   153.8     .12       0
  222.04     .08       0  252.24    .016       0  281.22     .06       0
  325.62     .08       0  360.12     .12       0
#XS Ineff= 2 , 0
                          188.64         1842.59
Permanent Ineff=
       F       F
Bank Sta=134.2,153.8
XS Rating Curve= 0 ,0
Exp/Cntr=0.3,0.1

Type RM Length L Ch R = 1 ,7103.7  ,191.7,196.3,198.6
XS GIS Cut Line= 3
     2034626.604      290743.297      2034747.75      290912.971
      2034848.01      291048.388
#Sta/Elev= 30
       0 1850.15     9.8 1846.63    32.6 1841.88    48.9 1839.23    71.7 1837.84
      88 1838.48   107.5 1838.06   117.3 1838.68   123.8 1838.52   130.3 1837.66
   143.3 1832.76   146.6 1831.96   159.6 1832.01   166.1 1831.39  170.21 1830.55
   182.4 1830.01  189.92 1830.52   198.7 1832.87  229.361832.368   240.9 1832.23
   257.1  1833.4  268.671833.638   273.3 1833.75   286.2 1835.25   302.4 1839.02
  313.641840.546   325.1 1842.58   341.3 1848.17   370.5 1861.12     377 1864.72
#Mann= 6 ,-1 , 0
       0     .12       0  170.21    .045       0  189.92     .12       0
  229.36    .016       0  268.67     .06       0  313.64     .12       0
#XS Ineff= 2 , 0
                          230.11         1835.04
Permanent Ineff=
       F       F
Bank Sta=170.21,189.92
XS Rating Curve= 0 ,0
Exp/Cntr=0.3,0.1

Type RM Length L Ch R = 1 ,6907.4  ,149.8,154.2,158.7
XS GIS Cut Line= 2
     2034495.528        290786.7     2034657.854      291095.727
#Sta/Elev= 30
       0  1849.3      13 1844.92    35.9 1839.02    48.9 1836.86    71.8 1834.48
    81.6 1833.58   107.7  1832.4   120.7  1830.7   143.5 1829.69   150.1 1828.66
   163.1 1827.73   176.2 1828.08  210.17 1827.88   221.8 1827.79   231.6 1826.55
   241.4    1826   250.5 1823.62   257.7 1822.29     261 1822.27   267.5 1823.21
  268.47 1823.92   270.8 1824.77   280.6 1830.34   309.9 1843.88   319.7 1849.68
   329.5 1850.61   332.8 1852.47     336 1854.83   339.3 1856.46   349.1 1858.94
#Mann= 4 ,-1 , 0
       0     .12       0  210.17    .016       0   250.5    .045       0
  268.47     .12       0
Bank Sta=250.5,268.47
XS Rating Curve= 0 ,0
Exp/Cntr=0.3,0.1

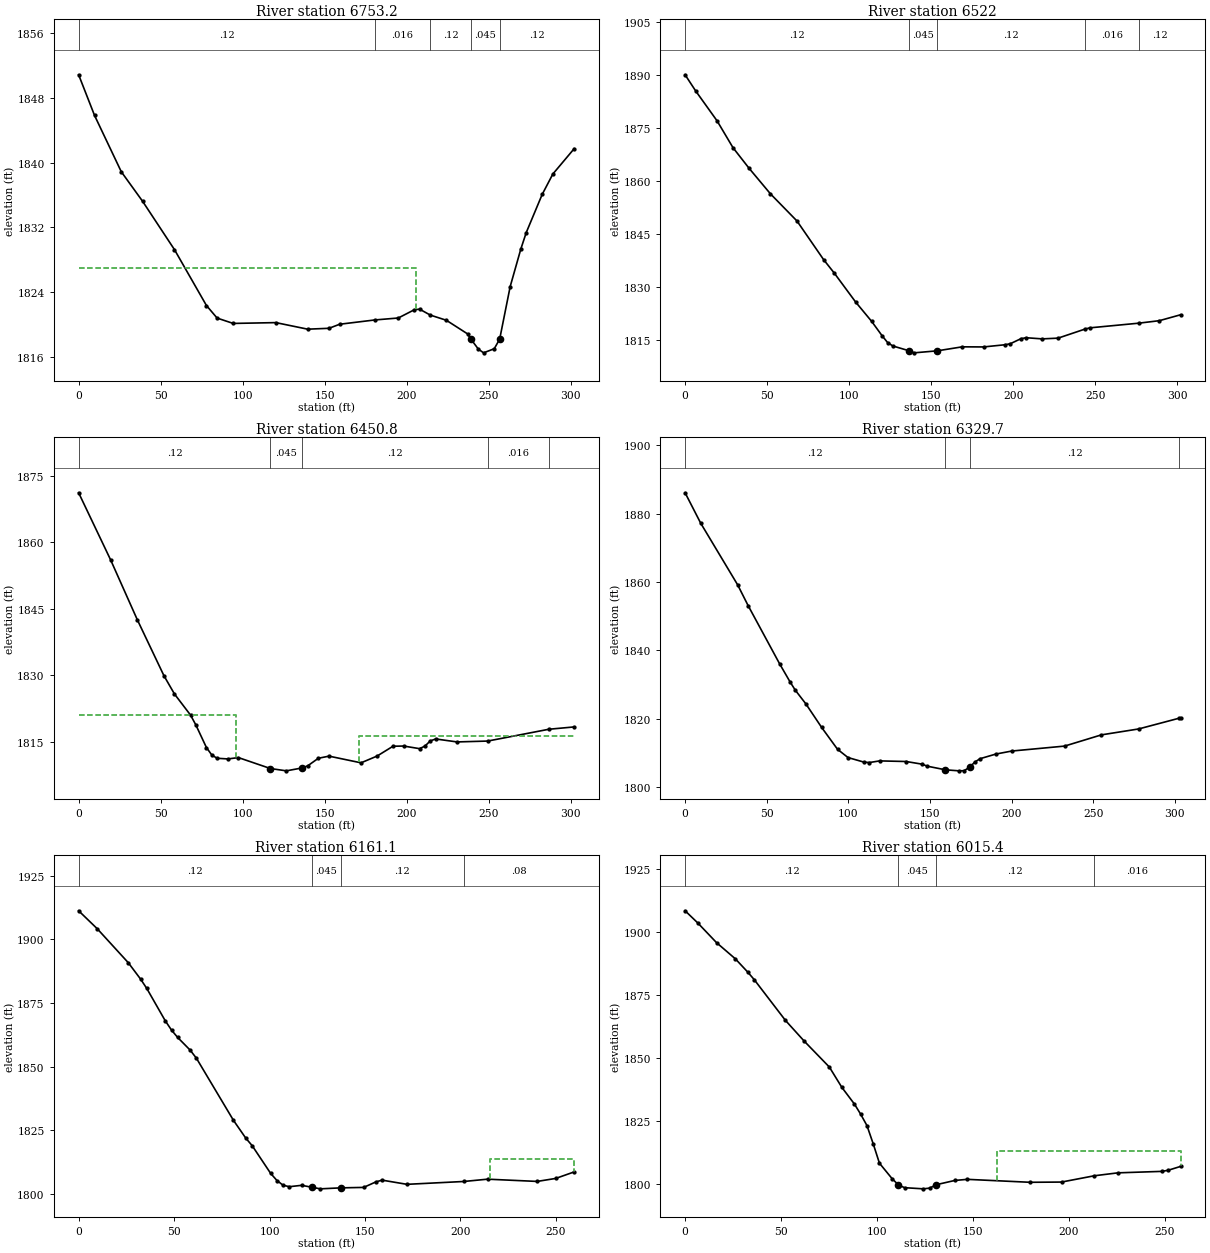
Type RM Length L Ch R = 1 ,6753.2  ,231.2,231.3,225.2
XS GIS Cut Line= 2
     2034402.646      290829.234     2034487.333      291119.134
#Sta/Elev= 30
       0 1850.84     9.7 1845.82      26 1838.87      39 1835.22    58.4 1829.26
    77.9 1822.36    84.4 1820.81    94.2 1820.15   120.2 1820.25   139.6 1819.44
   152.6 1819.55   159.1 1820.05  180.471820.578   194.8 1820.82   204.6 1821.84
   207.8 1821.91  214.331821.179   224.1 1820.54   237.1 1818.85     239 1818.23
   243.6 1816.98   246.8 1816.52   253.3 1817.03   256.6 1818.21     263  1824.7
   269.5 1829.34   272.8 1831.37   282.5 1836.07     289 1838.59     302 1841.72
#Mann= 5 ,-1 , 0
       0     .12       0  180.47    .016       0  214.33     .12       0
     239    .045       0   256.6     .12       0
#XS Ineff= 2 , 0
          205.82 1827.03
Permanent Ineff=
       F       F
Bank Sta=239,256.6
XS Rating Curve= 0 ,0
Exp/Cntr=0.3,0.1

Type RM Length L Ch R = 1 ,6522    ,71.1,71.2,76.9
XS GIS Cut Line= 2
     2034231.639      290817.081     2034316.326      291106.982
#Sta/Elev= 30
       0 1890.14     6.5 1885.53    19.5 1877.09    29.2  1869.5      39 1863.67
      52 1856.45    68.2 1848.75    84.4 1837.83    90.9 1834.02   103.9 1825.84
   113.7 1820.34   120.2 1816.19   123.4 1814.36   126.6 1813.38   136.4 1812.04
   139.6 1811.44   153.7 1812.01   168.9 1813.14   181.9 1813.11   194.8 1813.72
   198.1    1814   204.6 1815.43   207.8 1815.72   217.6 1815.39   227.3  1815.6
   243.91818.194   246.8 1818.52   276.41819.832     289 1820.54     302 1822.22
#Mann= 5 ,-1 , 0
       0     .12       0   136.4    .045       0   153.7     .12       0
   243.9    .016       0   276.4     .12       0
Bank Sta=136.4,153.7
XS Rating Curve= 0 ,0
Exp/Cntr=0.3,0.1

Type RM Length L Ch R = 1 ,6450.8  ,106.5,121.1,134
XS GIS Cut Line= 2
     2034165.667      290840.519     2034250.354      291130.419
#Sta/Elev= 30
       0 1871.21    19.5 1856.05    35.7 1842.58      52 1829.88    58.4 1825.76
    68.2 1820.99    71.4  1818.8    77.9 1813.65    81.2 1811.96    84.4 1811.24
    90.9 1811.09    97.4 1811.39   116.9 1808.92   126.6  1808.4   136.4 1809.07
   139.6 1809.53   146.1 1811.24   152.6 1811.72   172.1 1810.21   181.9 1811.74
   191.6 1813.96   198.1    1814   207.8 1813.41   211.1    1814   214.3 1815.16
   217.6  1815.6   230.6 1814.93  249.291815.126   286.61817.795     302 1818.32
#Mann= 5 ,-1 , 0
       0     .12       0   116.9    .045       0   136.4     .12       0
  249.29    .016       0   286.6     .06       0
#XS Ineff= 2 , 0
           95.95 1820.99  171.02         1816.31
Permanent Ineff=
       F       F
Bank Sta=116.9,136.4
XS Rating Curve= 0 ,0
Exp/Cntr=0.3,0.1

Type RM Length L Ch R = 1 ,6329.7  ,172.6,168.6,164.5
XS GIS Cut Line= 3
     2034118.792      290829.234     2034111.031      290906.027
     2034045.007      291122.637
#Sta/Elev= 30
       0 1886.09     9.6 1877.16    32.2 1859.15    38.6 1853.09    57.9 1836.05
    64.3 1830.76    67.5 1828.34      74 1824.32    83.6 1817.47    93.4 1811.03
    99.8 1808.62   109.5 1807.29   112.8 1807.15   119.2 1807.64   135.4 1807.46
   145.1 1806.69   148.4 1806.09   159.5 1805.03   167.8 1804.73     171 1804.77
   174.5 1805.89   177.5  1807.3   180.7 1808.28   190.4 1809.64   200.1 1810.52
   232.5 1811.97   255.1 1815.26   277.8 1816.98  302.591820.118   303.6  1820.2
#Mann= 4 ,-1 , 0
       0     .12       0   159.5    .045       0   174.5     .12       0
  302.59    .016       0
Bank Sta=159.5,174.5
XS Rating Curve= 0 ,0
Exp/Cntr=0.3,0.1

Type RM Length L Ch R = 1 ,6161.1  ,146.7,145.6,145
XS GIS Cut Line= 2
     2033961.674      290782.359     2033924.347      291039.304
#Sta/Elev= 30
       0 1911.16     9.7 1904.15      26 1890.79    32.5 1884.31    35.7 1880.68
    45.4 1867.97    48.7  1864.3    51.9 1861.44    58.4  1856.5    61.7 1853.31
    81.1 1828.94    87.6 1821.91    90.9    1819   100.6 1808.11   103.9 1805.31
   107.1 1803.47   110.4 1802.89   116.8 1803.43   122.2 1802.68   126.6 1802.05
   137.2 1802.43   149.3 1802.61   155.8  1804.8     159 1805.46     172 1803.82
  201.761804.936   214.2 1805.84   240.2 1804.96   249.9 1806.13   259.6 1808.69
#Mann= 4 ,-1 , 0
       0     .12       0   122.2    .045       0   137.2     .12       0
  201.76     .08       0
#XS Ineff= 2 , 0
                          215.62         1813.61
Permanent Ineff=
       F       F
Bank Sta=122.2,137.2
XS Rating Curve= 0 ,0
Exp/Cntr=0.3,0.1

Type RM Length L Ch R = 1 ,6015.4  ,84.9,84.2,82.8
XS GIS Cut Line= 2
     2033814.972      290761.526     2033788.931       291018.47
#Sta/Elev= 30
       0 1908.46     6.5 1903.71    16.4  1895.8    26.2 1889.38    32.7 1884.08
      36 1881.15    52.3 1864.94    62.1  1856.7    75.2 1846.41    81.7 1838.36
    88.3 1831.68    91.5 1827.72    94.8 1823.16    98.1 1815.83   101.3 1808.24
   107.9  1802.1   111.2 1799.62   114.4 1798.52   124.2 1798.06   127.5 1798.35
   130.8 1799.68   140.6 1801.39   147.1 1801.83   179.8 1800.66   196.2 1800.75
  213.291803.246   225.6 1804.41   248.4 1804.99   251.7 1805.41   258.3 1806.97
#Mann= 4 ,-1 , 0
       0     .12       0   111.2    .045       0   130.8     .12       0
  213.29    .016       0
#XS Ineff= 2 , 0
                          162.36         1813.17
Permanent Ineff=
       F       F
Bank Sta=111.2,130.8
XS Rating Curve= 0 ,0
Exp/Cntr=0.3,0.1

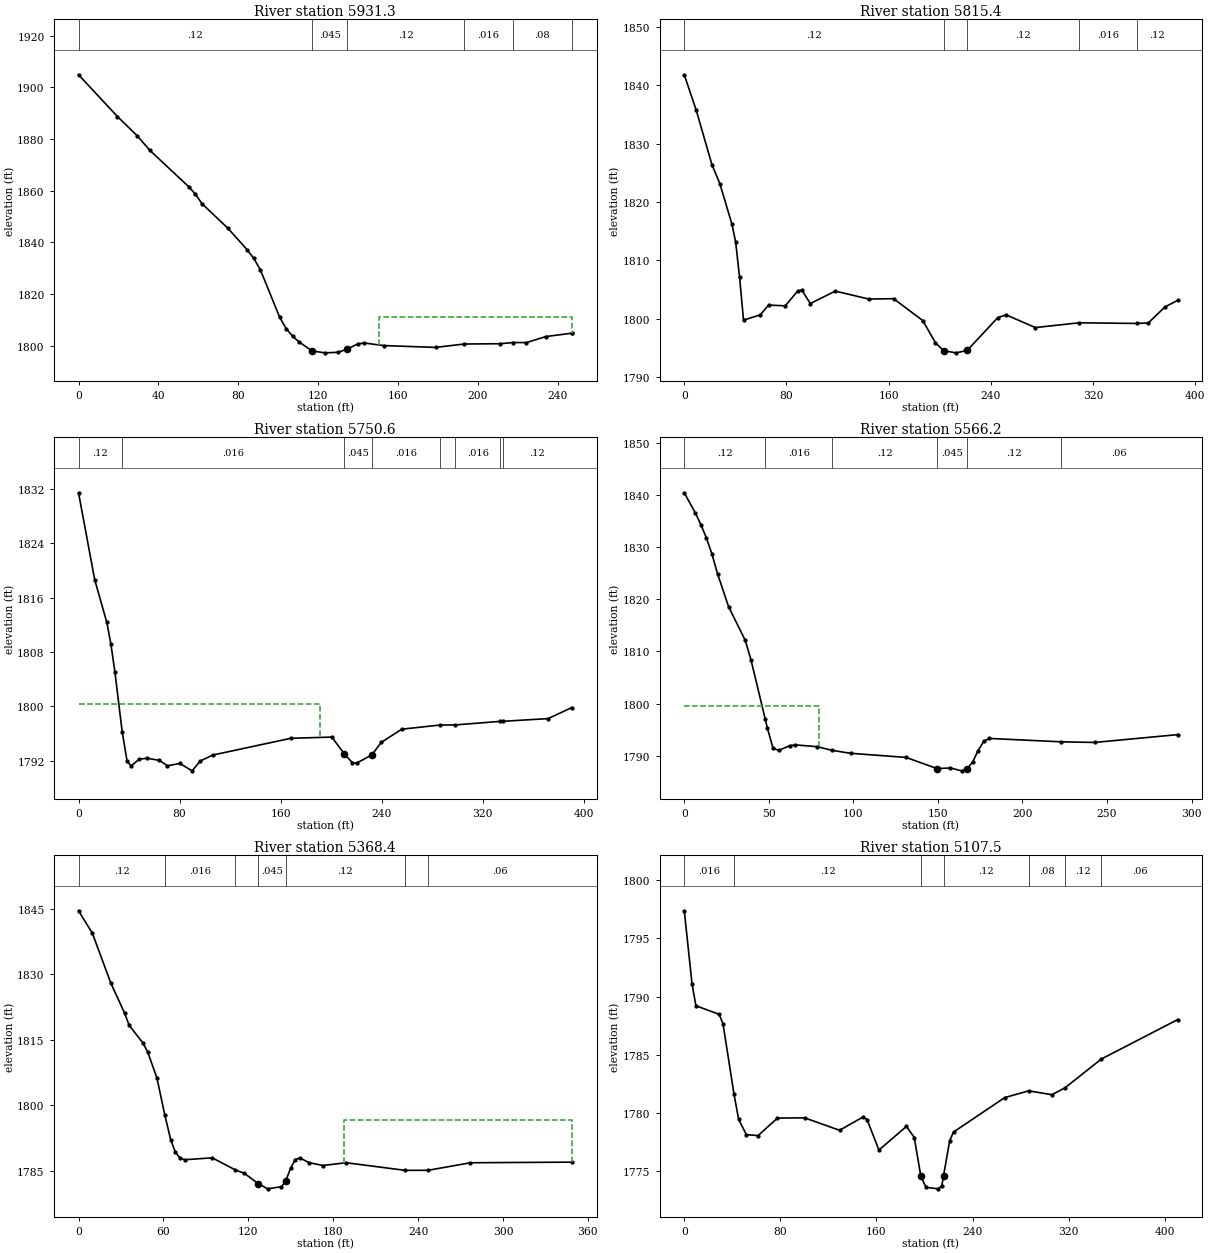
Type RM Length L Ch R = 1 ,5931.3  ,148.2,115.9,78.3
XS GIS Cut Line= 2
     2033726.043      290750.793     2033712.542      290997.637
#Sta/Elev= 30
       0  1904.8    19.5 1888.64    29.3 1881.28    35.8  1875.5    55.3  1861.4
    58.6 1858.56    61.8 1854.95    74.8 1845.42    84.6 1836.96    87.8 1833.74
    91.1 1829.33   100.8 1810.89   104.1 1806.48   107.3 1803.58   110.6 1801.32
   117.1 1797.86   123.6 1797.16   130.1 1797.37   134.4 1798.55   139.9  1800.6
   143.1 1800.97   152.9 1799.98   178.9 1799.26  193.251800.575   211.4 1800.69
  217.461801.148   224.4 1801.13   234.2 1803.47  247.041804.745   247.2 1804.75
#Mann= 6 ,-1 , 0
       0     .12       0   117.1    .045       0   134.4     .12       0
  193.25    .016       0  217.46     .08       0  247.04     .06       0
#XS Ineff= 2 , 0
                          150.57         1811.03
Permanent Ineff=
       F       F
Bank Sta=117.1,134.4
XS Rating Curve= 0 ,0
Exp/Cntr=0.3,0.1

Type RM Length L Ch R = 1 ,5815.4  ,56.3,64.8,78.8
XS GIS Cut Line= 4
     2033485.459      290720.554     2033467.229      290763.262
     2033671.917      290903.366     2033682.854      290994.512
#Sta/Elev= 30
       0 1841.79     9.3 1835.76    21.7 1826.36    27.9  1823.1    37.2 1816.29
    40.2 1813.19    43.3  1807.1    46.4 1799.74    59.5 1800.65      66 1802.32
    79.1  1802.2    88.9 1804.76    92.1 1804.88    98.7 1802.59   118.2 1804.72
   144.4 1803.36   163.9 1803.42   186.8 1799.66   196.6 1795.88   203.1 1794.49
   212.9 1794.14   221.5 1794.55   245.5 1800.18     252 1800.65   274.9 1798.47
  309.061799.289  354.091799.178   363.3 1799.26   376.4 1802.01   386.3 1803.14
#Mann= 5 ,-1 , 0
       0     .12       0   203.1    .045       0   221.5     .12       0
  309.06    .016       0  354.09     .12       0
Bank Sta=203.1,221.5
XS Rating Curve= 0 ,0
Exp/Cntr=0.3,0.1

Type RM Length L Ch R = 1 ,5750.6  ,148.4,184.4,220.1
XS GIS Cut Line= 4
     2033457.681      290714.825     2033422.091      290775.588
     2033634.243      290942.602      2033644.66      290991.561
#Sta/Elev= 30
       0 1831.44    12.8 1818.65    22.4 1812.35    25.6 1809.21    28.8 1805.05
   34.581796.236    38.4 1791.97    41.6 1791.22      48 1792.23    54.4 1792.36
      64 1792.05    70.4 1791.25    80.2  1791.6    89.9 1790.51    96.4 1791.96
   106.2 1792.83     168  1795.3   200.5 1795.48   210.3 1793.02   216.8  1791.7
   220.1 1791.65   232.1 1792.84   239.6 1794.69   255.8 1796.64  285.861797.248
   298.31797.271  333.611797.789   335.91797.802   371.7  1798.2   390.5 1799.83
#Mann= 8 ,-1 , 0
       0     .12       0   34.58    .016       0   210.3    .045       0
   232.1    .016       0  285.86     .08       0   298.3    .016       0
  333.61     .08       0   335.9     .12       0
#XS Ineff= 2 , 0
          191.48 1800.38
Permanent Ineff=
       F       F
Bank Sta=210.3,232.1
XS Rating Curve= 0 ,0
Exp/Cntr=0.3,0.1

Type RM Length L Ch R = 1 ,5566.2  ,194.4,197.8,200.2
XS GIS Cut Line= 2
     2033462.542       290701.63     2033295.875      290941.213
#Sta/Elev= 30
       0 1840.38     6.6 1836.48     9.8  1834.3    13.1 1831.71    16.4 1828.61
    19.7 1824.84    26.2 1818.56    36.1 1812.08    39.4 1808.43   47.891797.008
    49.2 1795.23    52.5 1791.45    55.8 1791.01    62.3 1791.91    65.6 1792.07
    78.7 1791.73   87.381791.029    98.4 1790.46   131.2 1789.67   149.5 1787.53
   157.4 1787.65     164  1787.1   167.2 1787.48   170.5 1788.75   173.8 1790.99
   177.1 1792.73   180.4 1793.31   222.81792.663   242.7 1792.54   291.8 1794.04
#Mann= 6 ,-1 , 0
       0     .12       0   47.89    .016       0   87.38     .12       0
   149.5    .045       0   167.2     .12       0   222.8     .06       0
#XS Ineff= 2 , 0
           79.69 1799.53
Permanent Ineff=
       F       F
Bank Sta=149.5,167.2
XS Rating Curve= 0 ,0
Exp/Cntr=0.3,0.1

Type RM Length L Ch R = 1 ,5368.4  ,271.9,260.9,249.1
XS GIS Cut Line= 2
     2033340.197      290575.732     2033109.729       290837.45
#Sta/Elev= 30
       0 1844.56     9.8 1839.41    22.8 1828.04    32.6  1821.1    35.8 1818.34
    45.6 1814.28    48.9 1812.21    55.4 1806.32   60.961797.839    65.2 1792.12
    68.4 1789.36    71.7 1787.94      75 1787.58    94.5 1788.02  110.741785.267
   117.3 1784.44   127.1 1782.11   133.6 1780.92   143.4 1781.41   146.4  1782.7
   149.9 1785.63   153.2 1787.61   156.4 1787.99     163 1786.91   172.7 1786.26
     189  1786.9  230.861785.153  247.061785.161     277 1786.89   348.7 1787.03
#Mann= 7 ,-1 , 0
       0     .12       0   60.96    .016       0  110.74     .12       0
   127.1    .045       0   146.4     .12       0  230.86     .08       0
  247.06     .06       0
#XS Ineff= 2 , 0
                          187.93         1796.76
Permanent Ineff=
       F       F
Bank Sta=127.1,146.4
XS Rating Curve= 0 ,0
Exp/Cntr=0.3,0.1

Type RM Length L Ch R = 1 ,5107.5  ,264.1,284.1,303.1
XS GIS Cut Line= 3
     2033117.975      290422.086     2033033.722      290515.866
     2032971.222      290793.644
#Sta/Elev= 30
       0 1797.37     6.5 1791.06     9.7 1789.21    29.1 1788.47    32.3 1787.64
   41.44 1781.59    45.3 1779.44    51.7 1778.14    61.4 1778.05    77.6 1779.56
   100.2 1779.58   129.3 1778.51     149 1779.66   152.2 1779.43   162.1 1776.81
     185 1778.85   191.5 1777.89     197 1774.55   201.3 1773.61   211.2 1773.48
   214.4 1773.73  215.91 1774.62     221 1777.62   224.2 1778.36   266.8 1781.32
  286.651781.897   306.1 1781.57  316.931782.153  347.211784.628   410.8 1788.02
#Mann= 7 ,-1 , 0
       0    .016       0   41.44     .12       0     197    .045       0
  215.91     .12       0  286.65     .08       0  316.93     .12       0
  347.21     .06       0
Bank Sta=197,215.91
XS Rating Curve= 0 ,0
Exp/Cntr=0.3,0.1

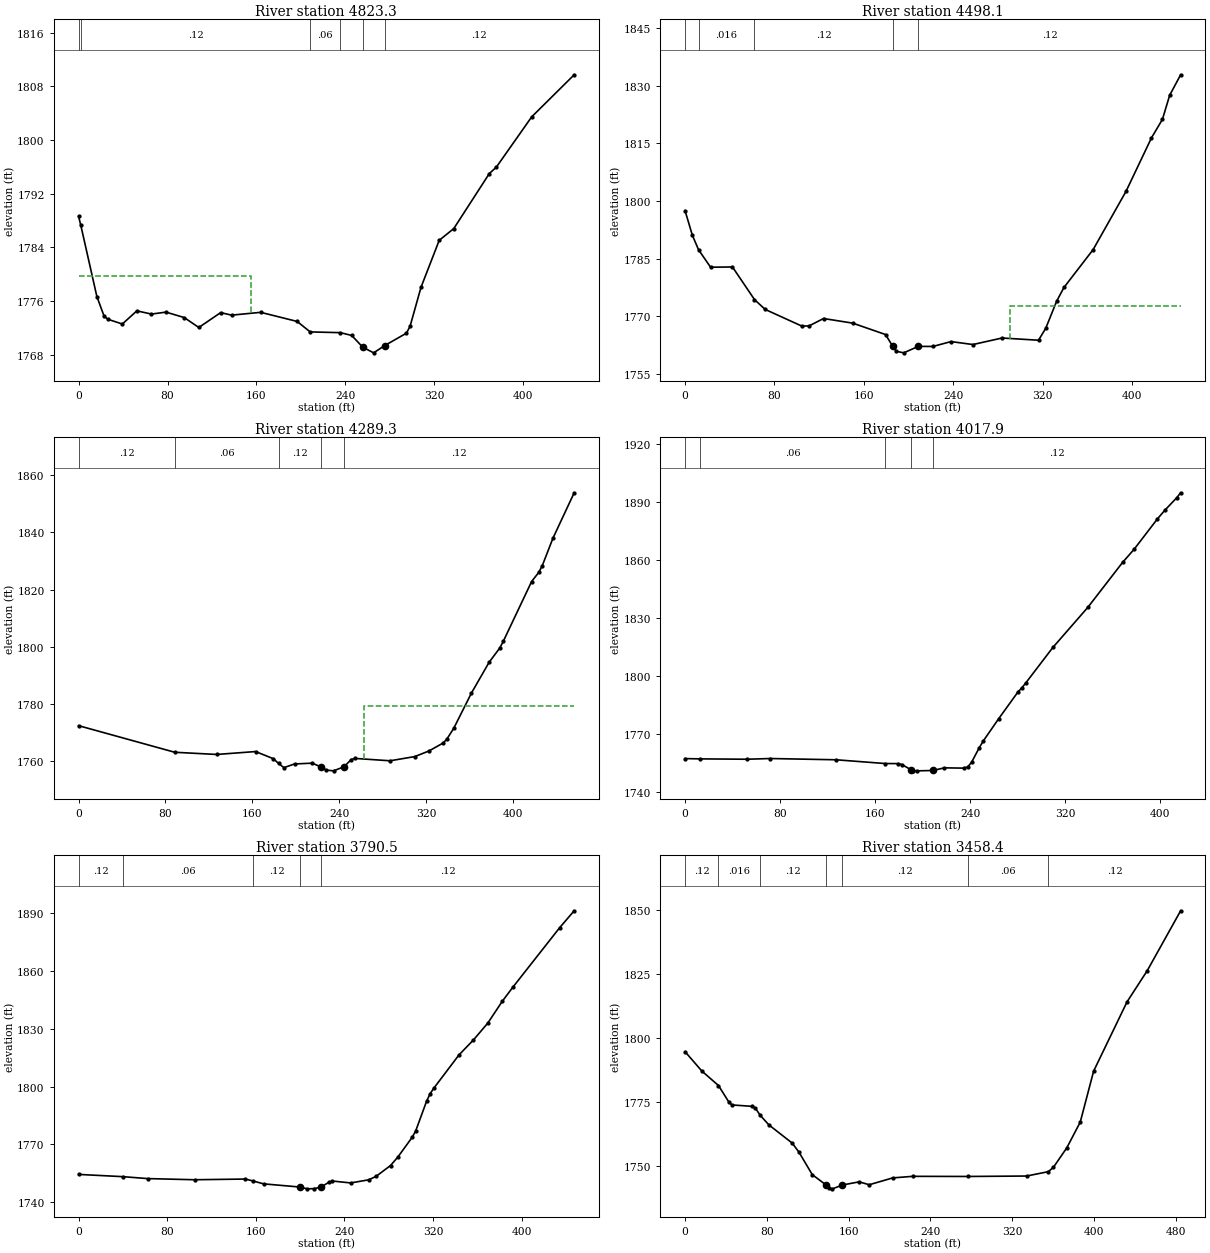
Type RM Length L Ch R = 1 ,4823.3  ,315.5,325.2,333.7
XS GIS Cut Line= 3
     2033022.438      290306.231     2032721.222      290472.463
      2032677.82      290564.477
#Sta/Elev= 30
       0 1788.61    1.981787.278    16.4 1776.68    22.9 1773.75    26.2 1773.29
    39.3 1772.58    52.4 1774.54    65.5 1774.06    78.6 1774.35      95 1773.54
   108.1 1772.06   127.8 1774.28   137.6  1773.9   163.8 1774.32   196.6 1772.96
  208.31  1771.4  235.471771.289   245.7 1770.87   255.6 1769.12   265.4 1768.28
   275.2 1769.35   294.9 1771.21   298.2 1772.26     308 1778.05   324.4 1785.06
   337.5 1786.81   369.5 1795.02   375.8 1795.97   407.6 1803.47   445.8 1809.74
#Mann= 6 ,-1 , 0
       0    .016       0    1.98     .12       0  208.31     .06       0
  235.47     .12       0   255.6    .045       0   275.2     .12       0
#XS Ineff= 2 , 0
          154.83 1779.75
Permanent Ineff=
       F       F
Bank Sta=255.6,275.2
XS Rating Curve= 0 ,0
Exp/Cntr=0.3,0.1

Type RM Length L Ch R = 1 ,4498.1  ,211.6,208.8,205.9
XS GIS Cut Line= 2
     2033003.826      290109.586      2032562.42      290152.555
#Sta/Elev= 30
       0 1797.41     6.5 1791.06      121787.302    22.8 1782.74    42.4  1782.8
   62.111774.316    71.7 1771.75   104.4 1767.43   110.9 1767.46   123.9 1769.39
     150 1768.19   179.4 1765.22   185.9 1762.12   189.1 1760.86   195.7 1760.46
   208.7 1762.14   221.8 1762.12     238 1763.39   257.6 1762.62   283.7 1764.32
   316.3 1763.74   322.8 1766.87   332.6 1773.94   339.1 1777.48   365.2 1787.33
   394.6 1802.47   417.4  1816.4   427.2 1821.21   433.7 1827.49   443.5 1832.81
#Mann= 5 ,-1 , 0
       0     .12       0      12    .016       0   62.11     .12       0
   185.9    .045       0   208.7     .12       0
#XS Ineff= 2 , 0
                          291.19         1772.54
Permanent Ineff=
       F       F
Bank Sta=185.9,208.7
XS Rating Curve= 0 ,0
Exp/Cntr=0.3,0.1

Type RM Length L Ch R = 1 ,4289.3  ,269,271.4,273.2
XS GIS Cut Line= 2
     2032957.385      289884.325     2032512.072      289984.586
#Sta/Elev= 30
       0 1772.49   88.591763.211   127.2 1762.45     163 1763.46   179.3 1760.98
  184.251759.298   189.1 1757.85   198.9 1759.13   215.2 1759.41   223.3 1758.09
   228.2 1756.98   234.8 1756.73   244.5 1758.15     251 1760.64   254.3 1761.07
   286.9 1760.24   309.7 1761.71   322.8 1763.68   335.8 1766.45   339.1 1767.74
   345.6 1771.61   361.9 1783.91   378.2 1794.66     388 1799.62   391.2 1801.94
   417.3 1822.81   423.9 1826.02   427.1 1828.33   436.9  1837.9   456.5 1853.79
#Mann= 5 ,-1 , 0
       0     .12       0   88.59     .06       0  184.25     .12       0
   223.3    .045       0   244.5     .12       0
#XS Ineff= 2 , 0
                          262.78         1779.29
Permanent Ineff=
       F       F
Bank Sta=223.3,244.5
XS Rating Curve= 0 ,0
Exp/Cntr=0.3,0.1

Type RM Length L Ch R = 1 ,4017.9  ,220.4,227.4,234.2
XS GIS Cut Line= 2
     2032858.427      289648.648     2032445.666      289708.544
#Sta/Elev= 30
       0 1757.51    12.81757.364    52.1 1757.18    71.7 1757.55   127.1  1756.9
  168.471754.957   179.2 1754.92   182.5 1754.43   189.8 1751.86   192.2 1751.34
   195.5 1751.18   208.5 1751.36   218.3 1752.73   234.6 1752.58   237.9 1753.22
   241.1 1755.56   247.6 1763.15   250.9 1766.56   263.9 1778.11   280.2    1792
   283.5 1794.14   286.7 1796.61   309.6 1815.04   338.9 1835.68   368.2 1858.96
     378 1865.83   397.5 1881.46     404 1886.11   413.8 1892.43   417.1 1895.01
#Mann= 5 ,-1 , 0
       0     .12       0    12.8     .06       0  168.47     .12       0
   189.8    .045       0   208.5     .12       0
Bank Sta=189.8,208.5
XS Rating Curve= 0 ,0
Exp/Cntr=0.3,0.1

Type RM Length L Ch R = 1 ,3790.5  ,349.6,332.1,313.2
XS GIS Cut Line= 3
     2032847.959      289501.977     2032571.917      289446.422
     2032415.667      289501.977
#Sta/Elev= 30
       0 1754.47      401753.308    62.2 1752.31   104.8 1751.71   150.6 1752.07
  157.54 1751.06     167 1749.58   199.7 1747.94   206.3    1747   212.8 1747.11
   218.6 1747.88   225.9 1750.38   229.2 1751.04   245.6 1750.06   261.9 1751.67
   268.5 1753.44   281.6 1759.08   288.1 1763.39   301.1 1773.65   304.3 1776.97
   314.1  1792.3   317.3  1796.2   320.6 1799.06   343.4 1816.36   356.4 1824.07
   369.4 1832.83   382.4 1844.06   392.1 1851.48   434.4 1882.33   447.4 1891.01
#Mann= 5 ,-1 , 0
       0     .12       0      40     .06       0  157.54     .12       0
   199.7    .045       0   218.6     .12       0
Bank Sta=199.7,218.6
XS Rating Curve= 0 ,0
Exp/Cntr=0.3,0.1

Type RM Length L Ch R = 1 ,3458.4  ,285.1,281.5,277.1
XS GIS Cut Line= 2
        2032779.      289084.846     2032380.562      289360.888
#Sta/Elev= 30
       0 1794.54    16.4 1786.99   32.671781.334    42.6 1775.02    45.8 1773.77
    65.5 1773.22    68.8 1772.48   73.531769.695    81.9    1766   104.8 1758.86
   111.4 1755.32   124.4 1746.56   137.6 1742.62   140.8 1741.23   144.1 1741.02
   153.9 1742.52   170.3 1743.75   180.1 1742.62   203.1 1745.29   222.7  1745.9
   276.4 1745.85   334.1 1746.02  355.251747.725   360.3 1749.44   373.4 1757.06
   386.5 1767.06   399.6 1786.98   432.3 1814.02     452 1826.15   484.7 1849.55
#Mann= 7 ,-1 , 0
       0     .12       0   32.67    .016       0   73.53     .12       0
   137.6    .045       0   153.9     .12       0   276.4     .06       0
  355.25     .12       0
Bank Sta=137.6,153.9
XS Rating Curve= 0 ,0
Exp/Cntr=0.3,0.1

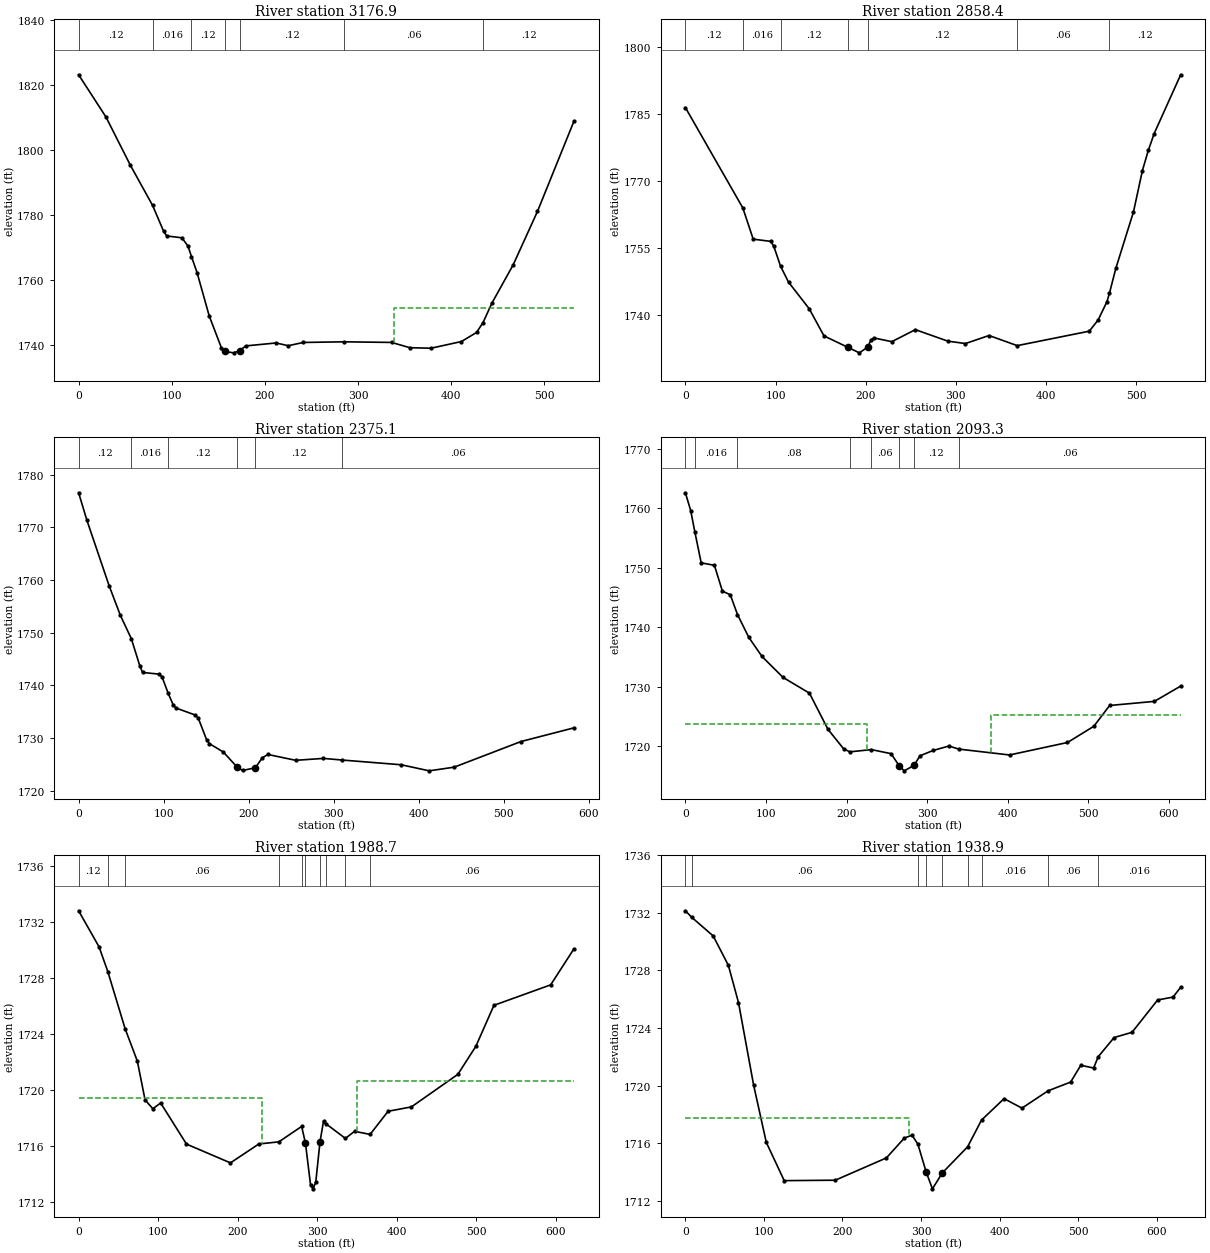
Type RM Length L Ch R = 1 ,3176.9  ,321.7,318.5,314.8
XS GIS Cut Line= 2
     2032657.906       288824.43     2032268.583      289186.409
#Sta/Elev= 30
       0 1823.04    29.4 1810.05    55.4 1795.34   79.391782.927    91.3 1774.94
    94.6 1773.55   110.9 1772.97   117.4 1770.43  121.141767.226   127.2 1762.23
   140.2 1748.97   153.3 1739.17   156.6 1738.08   166.3 1737.65   172.7 1738.31
   179.4 1739.78     212 1740.68     225 1739.84   241.3 1740.84  284.951741.035
   335.9 1740.85   355.5 1739.23   378.3 1739.07   410.9 1741.12   427.2 1743.92
  434.131746.961   443.6 1752.91   466.4 1764.65   492.5 1781.07   531.6 1808.72
#Mann= 7 ,-1 , 0
       0     .12       0   79.39    .016       0  121.14     .12       0
   156.6    .045       0   172.7     .12       0  284.95     .06       0
  434.13     .12       0
#XS Ineff= 2 , 0
                          338.35         1751.34
Permanent Ineff=
       F       F
Bank Sta=156.6,172.7
XS Rating Curve= 0 ,0
Exp/Cntr=0.3,0.1

Type RM Length L Ch R = 1 ,2858.4  ,485.6,483.3,479.3
XS GIS Cut Line= 2
     2032405.302      288597.867     2032061.552      289026.252
#Sta/Elev= 30
       0 1786.47   63.711763.991    75.2 1757.01    94.8 1756.51    98.1 1755.38
  105.561750.935   114.4 1747.38   137.3 1741.43   153.7 1735.35   179.8 1732.83
   192.9 1731.56  202.02 1732.82     206 1734.51   209.2 1734.89   228.9 1734.06
     255 1736.75     291 1734.18   310.6 1733.64   336.7 1735.44  367.991733.174
   447.9 1736.41   457.7 1738.92   467.5 1743.03  470.26 1744.92   477.3 1750.46
   496.9 1763.13   506.8 1772.37   513.3 1776.86   519.8 1780.64   549.2 1793.81
#Mann= 7 ,-1 , 0
       0     .12       0   63.71    .016       0  105.56     .12       0
   179.8    .045       0  202.02     .12       0  367.99     .06       0
  470.26     .12       0
Bank Sta=179.8,202.02
XS Rating Curve= 0 ,0
Exp/Cntr=0.3,0.1

Type RM Length L Ch R = 1 ,2375.1  ,290,281.8,272.7
XS GIS Cut Line= 2
     2032078.861      288251.977     2031775.725      288749.172
#Sta/Elev= 30
       0 1776.56     9.8 1771.31      36 1758.85    49.1 1753.28   61.961748.856
      72 1743.68    75.2 1742.44    94.9 1742.12    98.1 1741.59  105.341738.467
   111.2  1736.3   114.5 1735.69   137.4 1734.34   140.7 1733.76   150.5 1729.65
   153.8 1728.92   170.1 1727.34   186.5 1724.45   192.8 1723.83   207.8 1724.34
   215.9 1726.22   222.5 1726.87   255.2 1725.76   287.9 1726.12  309.631725.814
   379.5 1724.91   412.2 1723.76   441.6 1724.46   520.2 1729.33   582.3 1731.92
#Mann= 6 ,-1 , 0
       0     .12       0   61.96    .016       0  105.34     .12       0
   186.5    .045       0   207.8     .12       0  309.63     .06       0
Bank Sta=186.5,207.8
XS Rating Curve= 0 ,0
Exp/Cntr=0.3,0.1

Type RM Length L Ch R = 1 ,2093.3  ,112.8,104.6,95.9
XS GIS Cut Line= 3
     2031803.088      288121.956      2031740.32      288240.693
     2031663.497      288714.651
#Sta/Elev= 30
       0 1762.63     6.6 1759.62   11.671756.078    19.6 1750.84      36 1750.42
    45.9 1746.08    55.7 1745.46   64.611742.142    78.6 1738.31      95 1735.08
   121.2 1731.55   153.9  1728.9   176.8 1722.83   196.4 1719.52  204.011719.027
  230.751719.405   255.2 1718.72     265 1716.72   271.5 1715.83   283.5 1716.74
   291.1 1718.37   307.4 1719.26     327 1720.01  339.081719.489   402.1  1718.5
     474  1720.6   506.7 1723.33   526.3 1726.83   581.8 1727.52   614.4 1730.09
#Mann= 8 ,-1 , 0
       0     .08       0   11.67    .016       0   64.61     .08       0
  204.01    .016       0  230.75     .06       0     265    .045       0
   283.5     .12       0  339.08     .06       0
#XS Ineff= 2 , 0
          225.71 1723.76  378.69         1725.29
Permanent Ineff=
       F       F
Bank Sta=265,283.5
XS Rating Curve= 0 ,0
Exp/Cntr=0.3,0.1

Type RM Length L Ch R = 1 ,1988.7  ,50.6,49.7,48.9
XS GIS Cut Line= 4
     2031595.796      288098.127     2031567.151      288169.742
     2031632.247      288468.557     2031593.184      288705.536
#Sta/Elev= 30
       0 1732.78    25.7 1730.21   36.771728.439   58.471724.379    73.9 1722.06
    83.6  1719.3    93.4 1718.67   103.2 1719.08   135.7 1716.15     191 1714.81
   226.8 1716.16  251.861716.308  280.621717.407   285.4 1716.21   291.9  1713.2
   295.1 1712.96   298.4 1713.45  303.67  1716.3   308.1 1717.78  310.851717.613
  335.651716.555   347.2 1717.06  366.69 1716.84   389.4 1718.49   418.7  1718.8
   477.1 1721.12   499.8 1723.12   522.5 1726.04   593.9  1727.5   623.1 1730.06
#Mann= 10 ,-1 , 0
       0     .12       0   36.77     .08       0   58.47     .06       0
  251.86    .016       0  280.62     .08       0   285.4    .045       0
  303.67     .08       0  310.85     .06       0  335.65     .12       0
  366.69     .06       0
#XS Ineff= 2 , 0
          231.09 1719.43  350.59         1720.62
Permanent Ineff=
       F       F
Bank Sta=285.4,303.67
XS Rating Curve= 0 ,0
Exp/Cntr=0.3,0.1

Type RM Length L Ch R = 1 ,1938.9  ,312.2,326.7,339.7
XS GIS Cut Line= 4
     2031547.619      288089.013     2031512.463      288189.273
     2031578.861      288447.724     2031545.007      288702.932
#Sta/Elev= 30
       0 1732.15    7.911731.703    35.4  1730.4    54.7 1728.36    67.6 1725.77
    86.9 1720.02     103 1716.05   125.8 1713.39   190.8 1713.42   255.9 1714.97
   278.7 1716.35   288.5 1716.55  295.961715.929  306.53 1713.99   314.5 1712.82
   327.1 1713.93  359.291715.743     3771717.601   405.7 1719.09   428.5 1718.43
  461.711719.635   490.4 1720.24   503.4 1721.41   519.7 1721.22  525.531722.001
   545.8 1723.34   568.6  1723.7   601.2 1725.95   620.8 1726.15   630.5 1726.83
#Mann= 9 ,-1 , 0
       0     .12       0    7.91     .06       0  295.96    .016       0
  306.53    .045       0   327.1    .016       0  359.29     .06       0
     377    .016       0  461.71     .06       0  525.53    .016       0
#XS Ineff= 2 , 0
          284.38 1717.74
Permanent Ineff=
       F       F
Bank Sta=306.53,327.1
XS Rating Curve= 0 ,0
Exp/Cntr=0.3,0.1