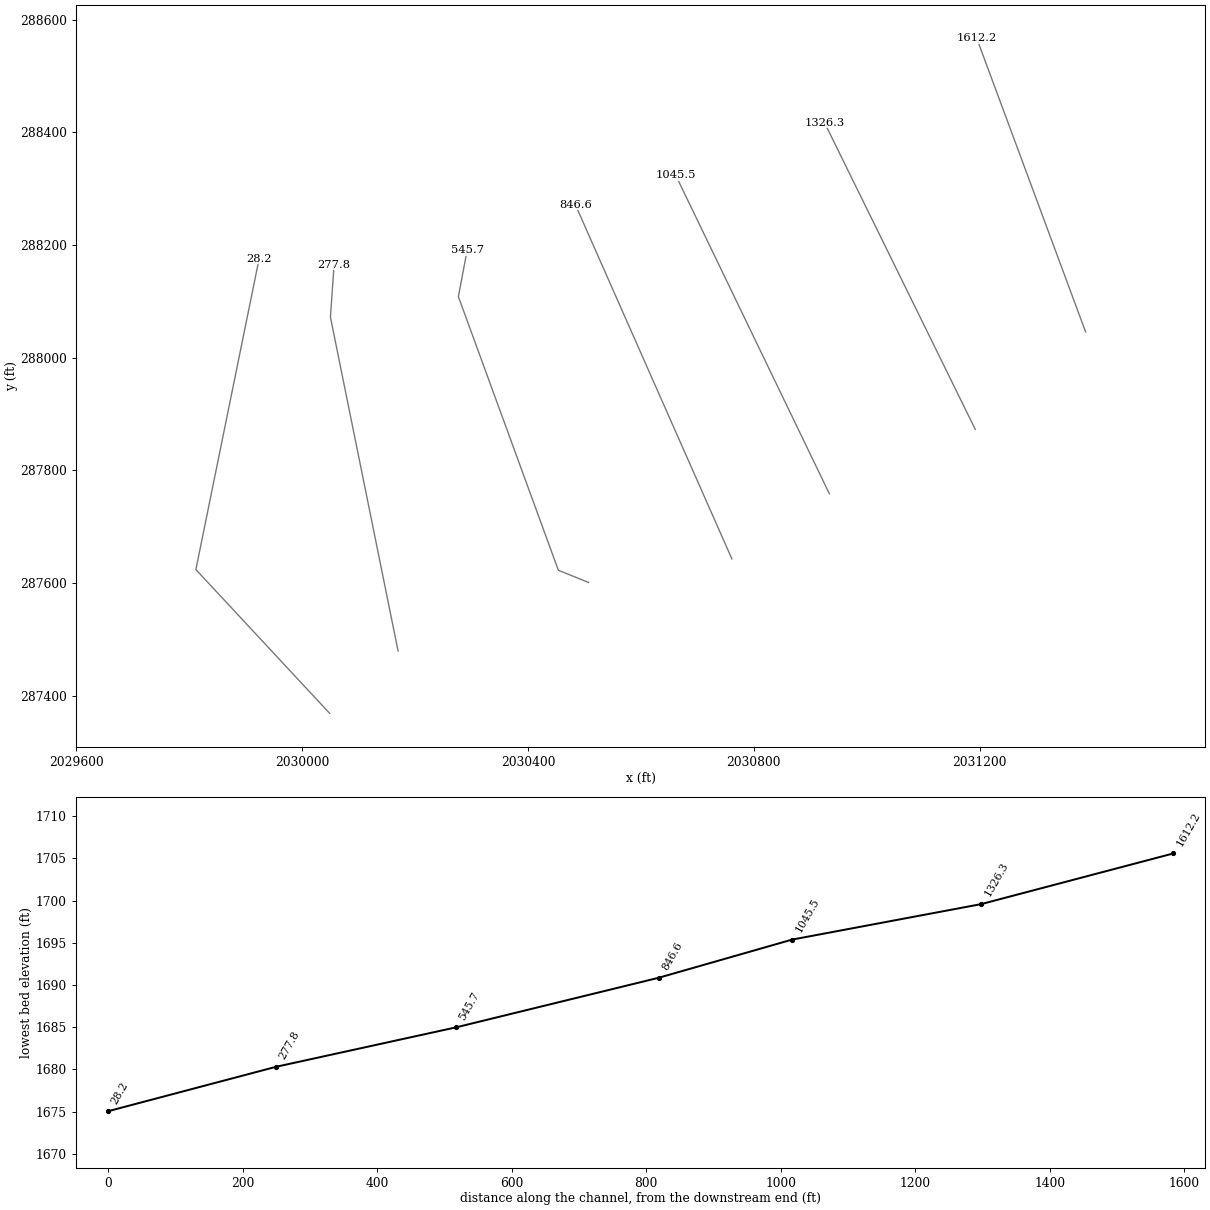
HEC-RAS study RDSPRBR.prj: RDSPRBR

--- RDSPRBR.g01 (geometry) --- (continued)

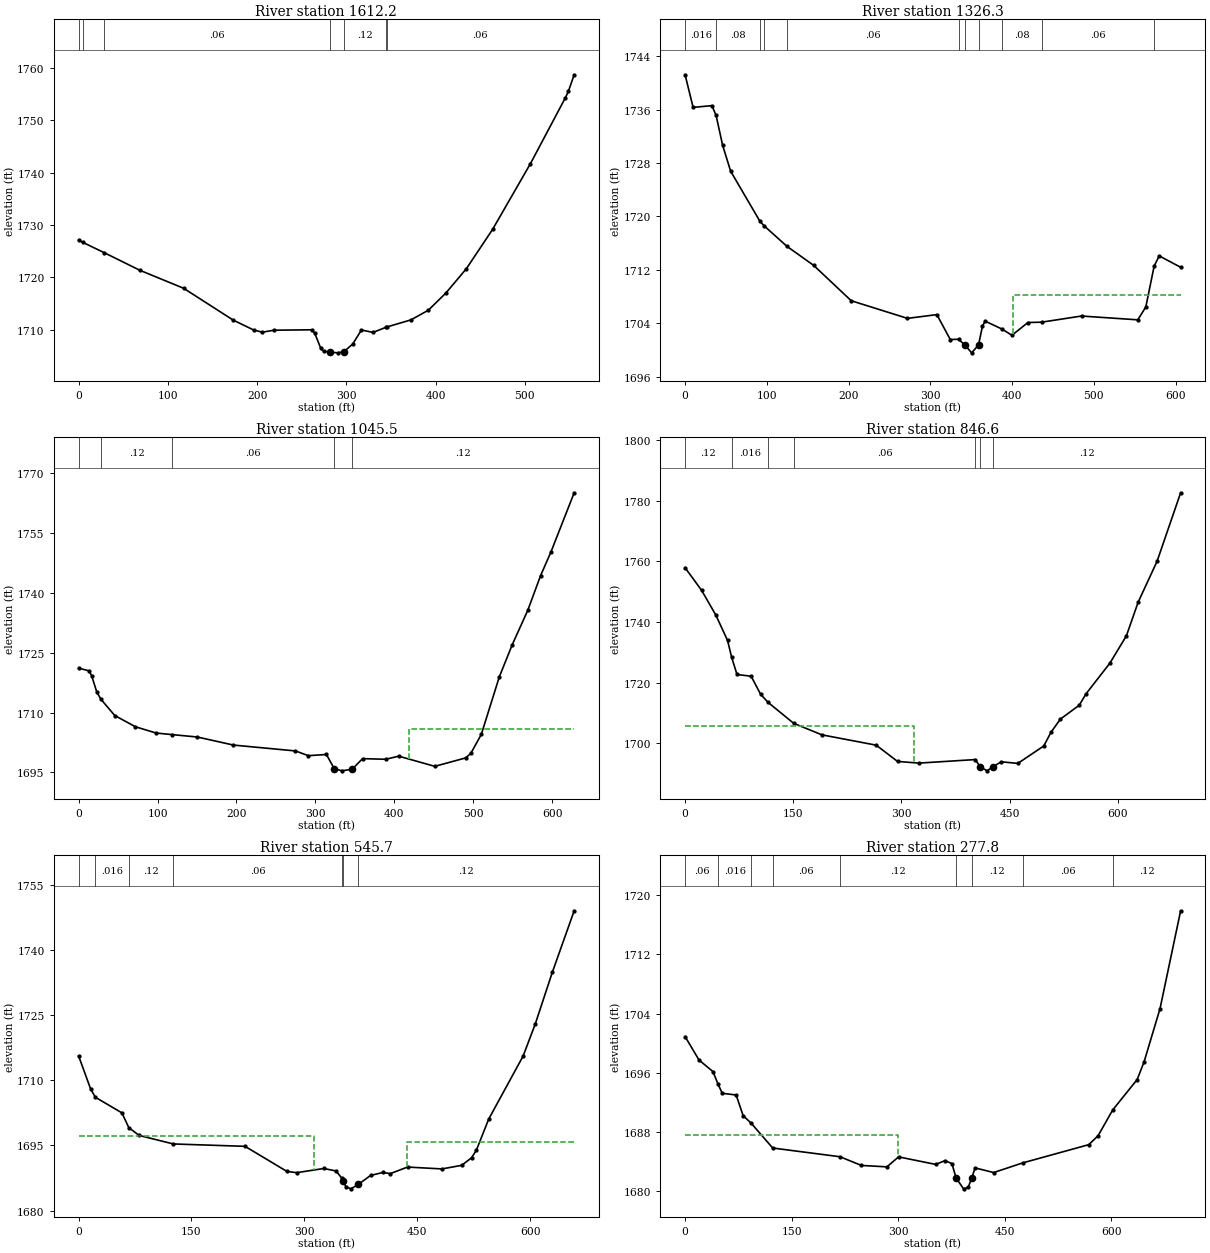
Type RM Length L Ch R = 1 ,1612.2  ,283.5,286,288
XS GIS Cut Line= 2
     2031387.463      288046.044     2031194.755      288566.877
#Sta/Elev= 30
       0 1727.15    4.551726.697   28.941724.698    68.6 1721.36   117.6 1717.93
   173.1 1711.86     196 1709.97   205.8 1709.54   218.9 1709.92   261.3    1710
   264.6 1709.33   271.1 1706.57   274.4 1705.91   281.2 1705.74   290.7  1705.6
   297.3 1705.83   307.1 1707.27   316.9 1709.96   329.9  1709.5  343.891710.442
  345.061710.524   372.4 1711.89     392 1713.75   411.6 1717.03   434.5 1721.66
   463.9 1729.17   506.3 1741.72   545.5 1754.31   548.8 1755.52   555.3 1758.68
#Mann= 7 ,-1 , 0
       0     .12       0    4.55     .08       0   28.94     .06       0
   281.2    .045       0   297.3     .12       0  343.89     .08       0
  345.06     .06       0
Bank Sta=281.2,297.3
XS Rating Curve= 0 ,0
Exp/Cntr=0.3,0.1

Type RM Length L Ch R = 1 ,1326.3  ,281,280.8,280.7
XS GIS Cut Line= 2
     2031192.151      287872.867     2030925.223      288417.138
#Sta/Elev= 30
       0 1741.21     9.8 1736.33    32.8 1736.59   37.941735.117    45.9 1730.66
    55.7 1726.78   91.511719.283   96.671718.603  124.411715.547   157.3 1712.68
   203.2 1707.39     272 1704.75     308 1705.31   324.4 1701.58  334.481701.626
   342.3 1700.75   350.6 1699.59  358.99 1700.78   363.7 1703.56     367 1704.34
   387.61703.152   399.8 1702.22   419.4 1704.13  436.071704.178     485  1705.1
   553.8 1704.53   563.6 1706.46  573.811712.583     580  1714.1   606.2  1712.4
#Mann= 11 ,-1 , 0
       0    .016       0   37.94     .08       0   91.51     .12       0
   96.67     .08       0  124.41     .06       0  334.48     .12       0
   342.3    .045       0  358.99     .12       0   387.6     .08       0
  436.07     .06       0  573.81     .12       0
#XS Ineff= 2 , 0
                           401.7         1708.27
Permanent Ineff=
       F       F
Bank Sta=342.3,358.99
XS Rating Curve= 0 ,0
Exp/Cntr=0.3,0.1

Type RM Length L Ch R = 1 ,1045.5  ,199.3,198.8,198.3
XS GIS Cut Line= 2
     2030933.809      287758.598      2030661.43      288324.376
#Sta/Elev= 30
       0 1721.15    13.1 1720.46    16.4 1719.29    22.9 1715.22   28.171713.354
    45.8 1709.26      72 1706.44    98.1 1704.87  118.421704.475   150.4 1703.87
   196.2 1701.85   274.7 1700.38   291.1 1699.19     314 1699.49   323.8 1695.96
   333.6 1695.39   346.6  1695.8   359.8 1698.45   389.2 1698.29   405.5 1699.07
   451.3 1696.52   490.6 1698.64   497.1 1699.83   510.2 1704.51   533.1 1718.98
   549.4    1727   569.1 1735.64   585.4 1744.36   598.5 1750.29   627.9 1765.11
#Mann= 5 ,-1 , 0
       0    .016       0   28.17     .12       0  118.42     .06       0
   323.8    .045       0   346.6     .12       0
#XS Ineff= 2 , 0
                          418.61            1706
Permanent Ineff=
       F       F
Bank Sta=323.8,346.6
XS Rating Curve= 0 ,0
Exp/Cntr=0.3,0.1

Type RM Length L Ch R = 1 ,846.6   ,301.7,301,298.7
XS GIS Cut Line= 2
     2030761.153      287643.036     2030483.809      288271.943
#Sta/Elev= 30
       0 1757.89    22.9 1750.44    42.6 1742.28    58.9  1733.9   64.591728.307
      72 1722.66    91.6 1722.09   104.7 1716.15     1151713.477  150.651706.532
   189.8 1702.74   265.1 1699.33   294.6 1693.97     324 1693.41  402.561694.581
   409.1 1692.21     419 1690.86   426.7  1692.2   438.6 1693.84   461.5 1693.32
   497.5 1699.07   507.3 1703.52   520.4 1707.91   546.6 1712.51   556.4 1716.38
   589.2 1726.41   612.1 1735.44   628.4 1746.55   654.6 1760.02   687.3 1782.64
#Mann= 7 ,-1 , 0
       0     .12       0   64.59    .016       0     115     .08       0
  150.65     .06       0  402.56     .12       0   409.1    .045       0
   426.7     .12       0
#XS Ineff= 2 , 0
          317.19 1705.68
Permanent Ineff=
       F       F
Bank Sta=409.1,426.7
XS Rating Curve= 0 ,0
Exp/Cntr=0.3,0.1

Type RM Length L Ch R = 1 ,545.7   ,271,267.9,264.4
XS GIS Cut Line= 4
     2030507.247       287601.37     2030453.869      287622.867
     2030276.786      288108.544     2030292.403      288191.213
#Sta/Elev= 30
       0 1715.56      16 1707.94   22.311706.049    57.5 1702.47   66.66 1699.08
    80.4 1697.28  125.921695.314   221.1 1694.77   276.8    1689   289.8 1688.71
   325.8 1689.67   342.2  1689.1  349.481687.489   351.3 1686.74   355.3 1685.47
   361.8 1684.99   371.6 1685.99     388 1688.07   404.4 1688.76   414.2 1688.49
   437.1    1690   482.9 1689.57   509.1  1690.4   522.2 1692.13   528.7 1693.91
     545 1701.04   590.7 1715.52   606.9 1722.92   629.5 1734.78   658.6 1748.96
#Mann= 7 ,-1 , 0
       0     .12       0   22.31    .016       0   66.66     .12       0
  125.92     .06       0  349.48     .12       0   351.3    .045       0
   371.6     .12       0
#XS Ineff= 2 , 0
          313.21 1697.21  436.51         1695.87
Permanent Ineff=
       F       F
Bank Sta=351.3,371.6
XS Rating Curve= 0 ,0
Exp/Cntr=0.3,0.1

Type RM Length L Ch R = 1 ,277.8   ,256.8,249.6,241
XS GIS Cut Line= 3
     2030170.015      287479.638     2030050.223      288072.086
     2030056.726      288165.172
#Sta/Elev= 30
       0 1700.88    19.6 1697.72    39.2 1696.15   46.241694.498    52.3 1693.22
    71.9 1692.99    81.7 1690.21   93.231689.156  123.371685.825   218.11684.647
   248.3 1683.47   284.2 1683.28   300.6 1684.63   352.9 1683.61   365.9 1684.12
   375.7 1683.73  381.57 1681.78   392.1 1680.31   398.6  1680.5  403.58 1681.76
   408.4 1683.14   434.5 1682.51  475.141683.808   568.5 1686.28   581.6 1687.49
  602.191690.974   636.6 1695.08   646.3 1697.46   668.8 1704.67   697.8 1717.88
#Mann= 9 ,-1 , 0
       0     .06       0   46.24    .016       0   93.23     .08       0
  123.37     .06       0   218.1     .12       0  381.57    .045       0
  403.58     .12       0  475.14     .06       0  602.19     .12       0
#XS Ineff= 2 , 0
          300.28 1687.59
Permanent Ineff=
       F       F
Bank Sta=381.57,403.58
XS Rating Curve= 0 ,0
Exp/Cntr=0.3,0.1

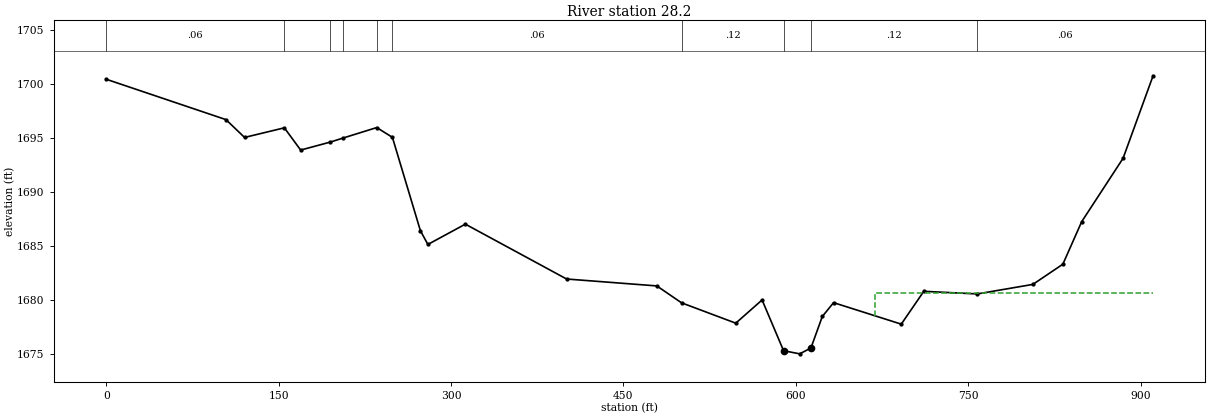
Type RM Length L Ch R = 1 ,28.2    ,36.5,28.2,19.6
XS GIS Cut Line= 3
     2030048.921      287368.961     2029811.942      287624.169
     2029923.913      288175.588
#Sta/Elev= 30
       0 1700.48   104.2 1696.74   120.4 1695.09  155.02 1695.98   169.2 1693.92
  195.121694.664  205.621695.018  235.421696.005  249.031695.099   273.4 1686.45
   279.9 1685.18   312.5 1687.06   400.6 1681.98   479.1 1681.34  500.611679.775
   547.8 1677.89   570.7 1680.04   589.4 1675.34   603.4 1675.05   613.2 1675.59
   623.1 1678.51   632.9 1679.79   691.8  1677.8   711.4 1680.84  757.941680.597
   806.3 1681.48   832.4 1683.35   848.8 1687.29   884.8 1693.16   910.9  1700.8
#Mann= 10 ,-1 , 0
       0     .06       0  155.02    .016       0  195.12     .08       0
  205.62     .06       0  235.42     .12       0  249.03     .06       0
  500.61     .12       0   589.4    .045       0   613.2     .12       0
  757.94     .06       0
#XS Ineff= 2 , 0
                          669.03         1680.73
Permanent Ineff=
       F       F
Bank Sta=589.4,613.2
XS Rating Curve= 0 ,0
Exp/Cntr=0.3,0.1

Chan Stop Cuts=-1
Use User Specified Reach Order=0
Composite Channel Slope=5